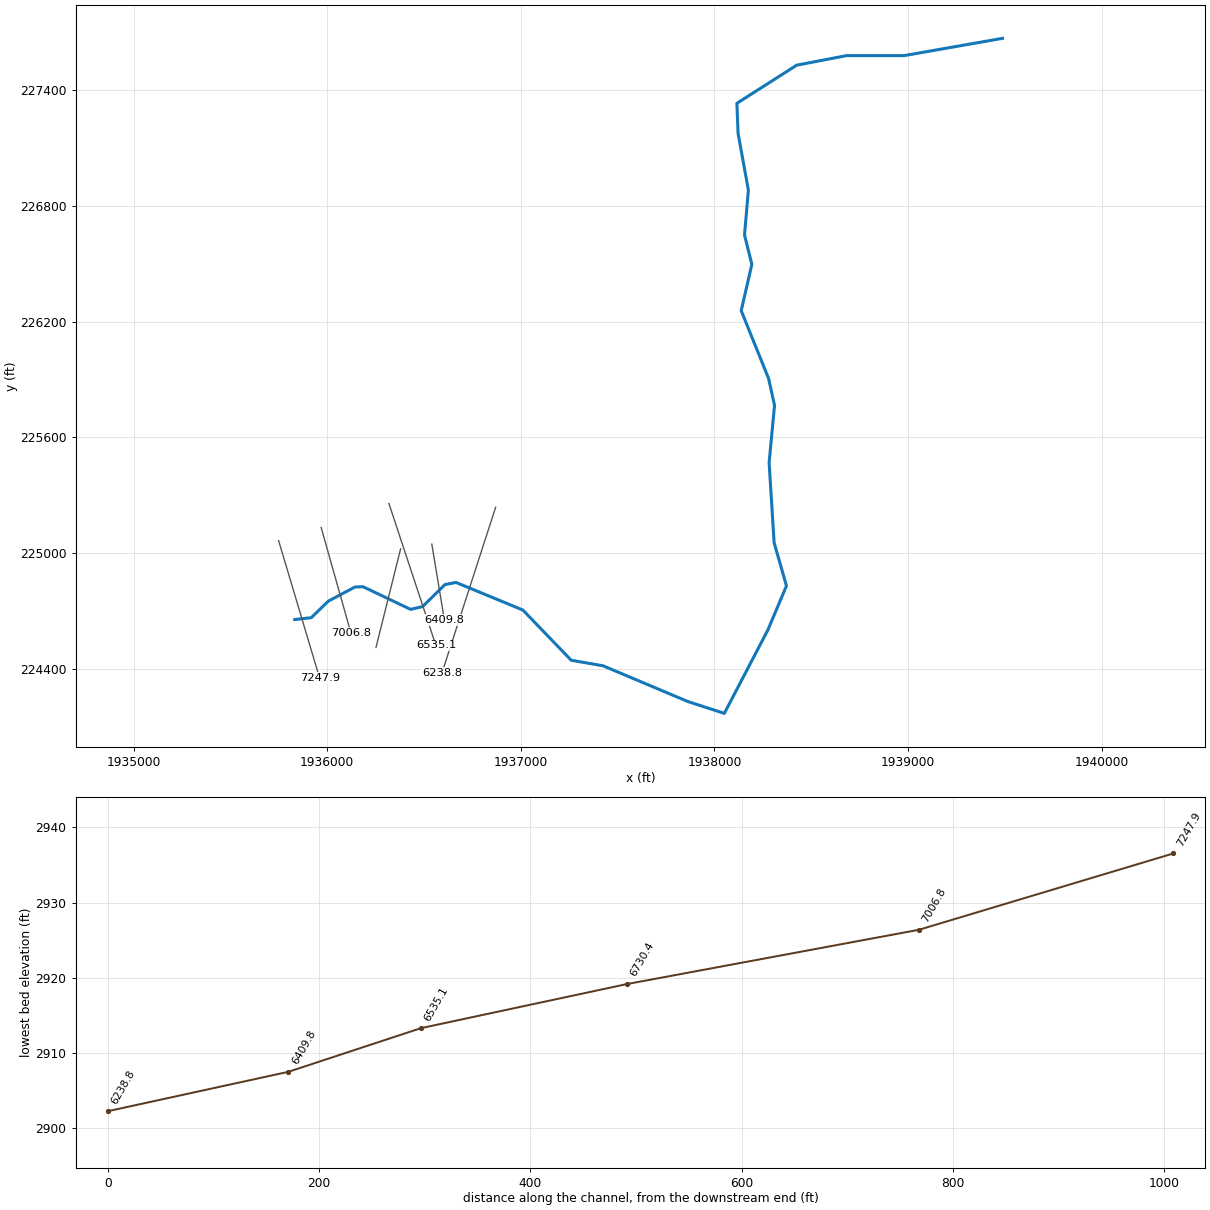
--- McKnnyBr.prj (project) ---

Proj Title=McKnnyBr
Current Plan=p01
Default Exp/Contr=0,0
English Units
Geom File=g01
Flow File=f01
Plan File=p01
BEGIN DESCRIPTION:
END DESCRIPTION:
DSS Export Rating Curves= 0
DSS Export Rating Curve Sorted= 0
DSS Export Volume Flow Curves= 0
DXF OffsetX= 0
DXF OffsetY= 0
DXF ScaleX= 0
DXF ScaleY= 0

--- McKnnyBr.p01 (plan) ---

Plan Title=Floodplain
Program Version=4.00
Geom File=g01
Flow File=f01
K Sum by GR=0
Std Step Tol=0.01
Critical Tol=0.01
Num of Std Step Trials=20
Max Error Tol=0.3
Flow Tol Ratio=0.001
Split Flow NTrial=30
Split Flow Tol=0.02
Split Flow Ratio=0.02
Log Output Level=0
Friction Slope Method=1
Unsteady Friction Slope Method=2
Unsteady Bridges Friction Slope Method=1
Global Log Level=0
CheckData=False
Run HTab=0
Run UNet=0
Run PostProcess=0
UNET Theta=0
UNET Theta Warmup=0
UNET ZTol=0
UNET ZSATol=0
UNET MxIter=0
UNET MaxInSteps=0
UNET DtIC=0
UNET DtMin=0
UNET MaxCRTS=0
UNET WFStab=0
UNET SFStab=0
UNET WFX=0
UNET SFX=0
UNET DSS MLevel=0
UNET DZMax Abort=0
UNET Convert EG Bridges=0
UNET Use Existing IB Tables=0
UNET Froude Limit=0
UNET Froude Power=0
Write IC File=0
Echo Input=False
Echo Output=False
Write Detailed=0

--- McKnnyBr.f01 (steady flow) ---

Flow Title=NFF Regression Equation
Program Version=4.00
Number of Profiles=1
Profile Names=P100yr
River Rch & RM=McKnnyBr,Main      ,7247.9
647.6691
Boundary for River Rch & Prof#=McKnnyBr,Main      ,1
Up Type=0
Dn Type=3
Dn Slope=0.034515

--- McKnnyBr.g01 (geometry) ---

Geom Title=USGS 3m DEM
Program Version=4.10

River Reach=McKnnyBr        ,Main
Reach XY= 30
     1935832.241      224657.836      1935917.68      224667.298
     1936005.946      224753.008       1936143.9      224826.258
     1936185.408      224827.479     1936430.794      224710.279
     1936493.056      224724.929     1936607.814      224838.466
     1936665.358      224849.646     1937010.374       224707.01
     1937260.389      224446.914     1937424.357      224418.491
     1937862.331      224233.424     1938050.845      224172.108
     1938275.755       224603.71     1938371.711      224831.911
     1938308.047      225055.775     1938282.215       225470.57
      1938310.12      225765.968     1938279.402      225905.561
     1938138.012      226256.085     1938193.024      226495.837
     1938155.234       226647.43     1938175.075      226879.649
     1938121.944      227173.681     1938115.767      227329.171
     1938424.581      227526.577     1938682.385      227576.151
      1938979.85      227576.147     1939487.366      227665.516

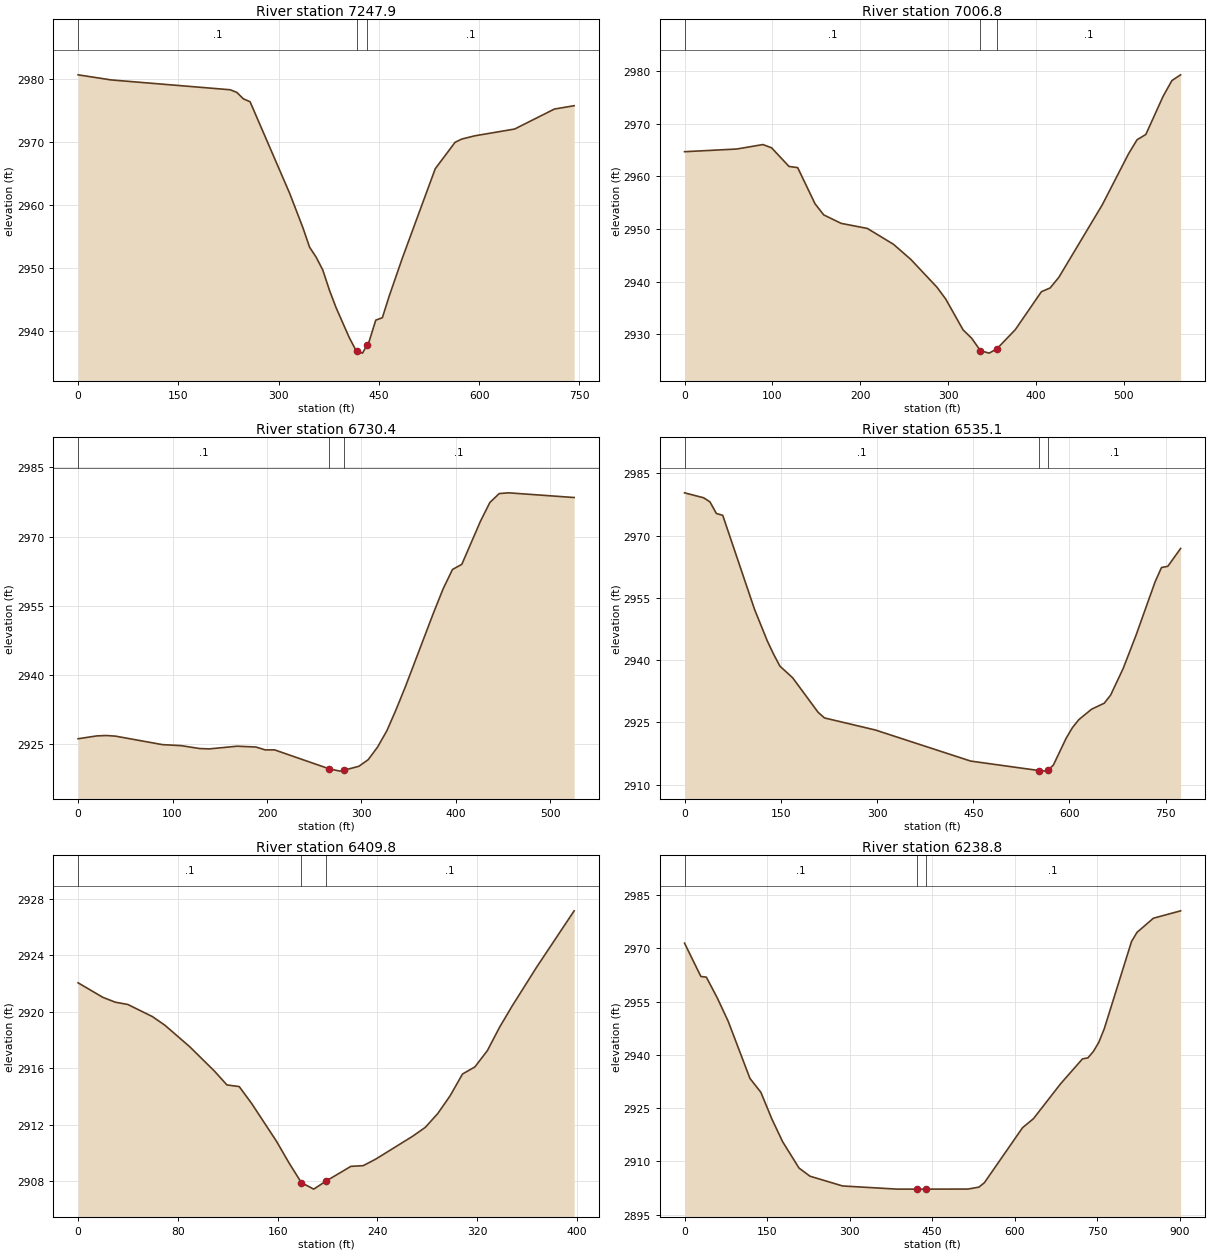
Type RM Length L Ch R = 1 ,7247.9  ,240.9,240.8,240.7
XS GIS Cut Line= 2
     1935749.081      225066.508     1935960.803      224355.206
#Sta/Elev= 30
       0 2980.69    49.5 2979.88   227.6 2978.32   237.5  2977.9   247.4 2976.87
   257.3 2976.42   316.6 2961.87   336.4 2956.42   346.3 2953.35   356.2 2951.75
   366.1 2949.72     376 2946.53   385.9 2943.77   405.7    2939   415.6    2937
   417.6 2936.91   425.5 2936.54   432.6 2937.87   435.4 2938.39   445.3 2941.77
   455.2 2942.16   465.1 2945.49   484.9 2951.56   534.3 2965.79     564 2969.99
   573.9  2970.5   593.7 2971.02   653.1 2972.09   712.5 2975.26   742.1 2975.79
#Mann= 3 , 0 , 0
       0      .1       0   417.6    .045       0   432.6      .1       0
Bank Sta=417.6,432.6
XS Rating Curve= 0 ,0
Exp/Cntr=0.3,0.1

Type RM Length L Ch R = 1 ,7006.8  ,287.2,276.6,264.7
XS GIS Cut Line= 2
     1935968.915       225134.11     1936121.925      224590.435
#Sta/Elev= 30
       0  2964.7    59.4 2965.21    89.2 2966.06    99.1 2965.44   118.9  2961.9
   128.8 2961.67   148.6 2954.78   158.5 2952.67   178.4 2951.06   208.1  2950.1
   237.8 2947.09   257.6 2944.21   287.4 2938.91   297.3 2936.68   317.1  2930.8
     327 2929.18   336.9 2926.83   346.8 2926.37   355.5 2927.17   376.5 2930.82
   406.3 2938.06   416.2 2938.77   426.1 2940.78   475.6 2954.59   505.3 2964.24
   515.2 2966.97   525.2 2967.98     545 2975.29   554.9 2978.24   564.8 2979.33
#Mann= 3 , 0 , 0
       0      .1       0   336.9    .045       0   355.5      .1       0
Bank Sta=336.9,355.5
XS Rating Curve= 0 ,0
Exp/Cntr=0.3,0.1

Type RM Length L Ch R = 1 ,6730.4  ,185,194.8,207.1
XS GIS Cut Line= 2
     1936379.112      225023.421     1936252.146       224513.93
#Sta/Elev= 30
       0 2926.15    19.8 2926.77    29.7 2926.86    39.6 2926.72    89.2 2924.88
     109 2924.66   128.8 2924.03   138.7 2923.95   168.4 2924.54   188.2 2924.36
   198.1 2923.74     208 2923.74   266.1 2919.61   277.4 2919.13   281.1 2919.31
   297.2 2920.18   307.1 2921.62     317 2924.34   326.9 2927.91   336.8 2932.57
   346.8 2937.62   376.5 2953.61   386.4 2958.67   396.3 2962.87   406.2 2963.99
     426 2973.37   435.9 2977.41   445.8 2979.34   455.7  2979.5   525.1 2978.48
#Mann= 3 , 0 , 0
       0      .1       0   266.1    .045       0   281.1      .1       0
Bank Sta=266.1,281.1
XS Rating Curve= 0 ,0
Exp/Cntr=0.3,0.1

Type RM Length L Ch R = 1 ,6535.1  ,128.1,125.3,117.5
XS GIS Cut Line= 2
     1936318.885       225257.82     1936561.422      224523.696
#Sta/Elev= 30
       0 2980.32    29.7 2979.13    39.6 2978.14    49.6 2975.34    59.5  2974.9
     109 2952.28   128.9 2944.66   138.8 2941.43   148.7 2938.55   168.5 2935.75
   208.2 2927.43   218.1 2926.08   297.4 2923.17     446 2915.68     552 2913.41
     565 2913.26     567 2913.56   574.9 2914.73   594.7 2921.16   604.6 2923.75
   614.6 2925.67   634.4 2928.18   654.2 2929.63   664.1 2931.58   683.9 2938.08
   703.8 2946.04   733.5  2958.9   743.4 2962.32   753.3 2962.62   773.2 2966.92
#Mann= 3 , 0 , 0
       0      .1       0     552    .045       0     567      .1       0
Bank Sta=552,567
XS Rating Curve= 0 ,0
Exp/Cntr=0.3,0.1

Type RM Length L Ch R = 1 ,6409.8  ,181.6,171,164.4
XS GIS Cut Line= 2
     1936540.261      225047.838     1936605.372      224655.546
#Sta/Elev= 30
       0 2922.04    19.9 2921.01    29.8 2920.67    39.8 2920.51    59.6 2919.65
    69.6 2919.04    89.5 2917.52   109.4 2915.79   119.3 2914.82   129.2  2914.7
   139.2  2913.5   159.1 2910.83     169 2909.32     179 2907.91   188.9 2907.45
   198.8 2908.02   218.7 2909.06   228.6 2909.11   238.6 2909.57   268.4  2911.2
   278.4 2911.82   288.3 2912.79   298.2 2914.04   308.2 2915.59   318.1 2916.09
   328.1 2917.24     338 2918.91     348  2920.4   367.8 2923.17   397.7 2927.13
#Mann= 3 , 0 , 0
       0      .1       0     179    .045       0   198.8      .1       0
Bank Sta=179,198.8
XS Rating Curve= 0 ,0
Exp/Cntr=0.3,0.1

Type RM Length L Ch R = 1 ,6238.8  ,6219.2,6235.7,6249
XS GIS Cut Line= 2
     1936870.058        225238.9     1936592.535      224380.767
#Sta/Elev= 30
       0 2971.46    29.7 2962.08    39.6  2961.9    59.5 2956.04    79.3 2949.48
   118.9 2933.38   138.8 2929.45   158.6    2922   178.4 2915.53   208.1 2908.14
     228 2905.84   287.4 2903.09   386.5  2902.2   423.4  2902.2   438.4  2902.2
   515.4 2902.22   535.2 2902.77   545.1    2904   614.5  2919.5   634.3 2922.03
   683.8 2931.89   723.5 2938.88   733.4 2939.17   743.3 2940.97   753.2 2943.55
   763.1 2947.37   812.7 2971.95   822.6  2974.5   852.3 2978.48   901.9 2980.57
#Mann= 3 , 0 , 0
       0      .1       0   423.4    .045       0   438.4      .1       0
Bank Sta=423.4,438.4
XS Rating Curve= 0 ,0
Exp/Cntr=0.3,0.1

Chan Stop Cuts=-1
Use User Specified Reach Order=0
Composite Channel Slope=5